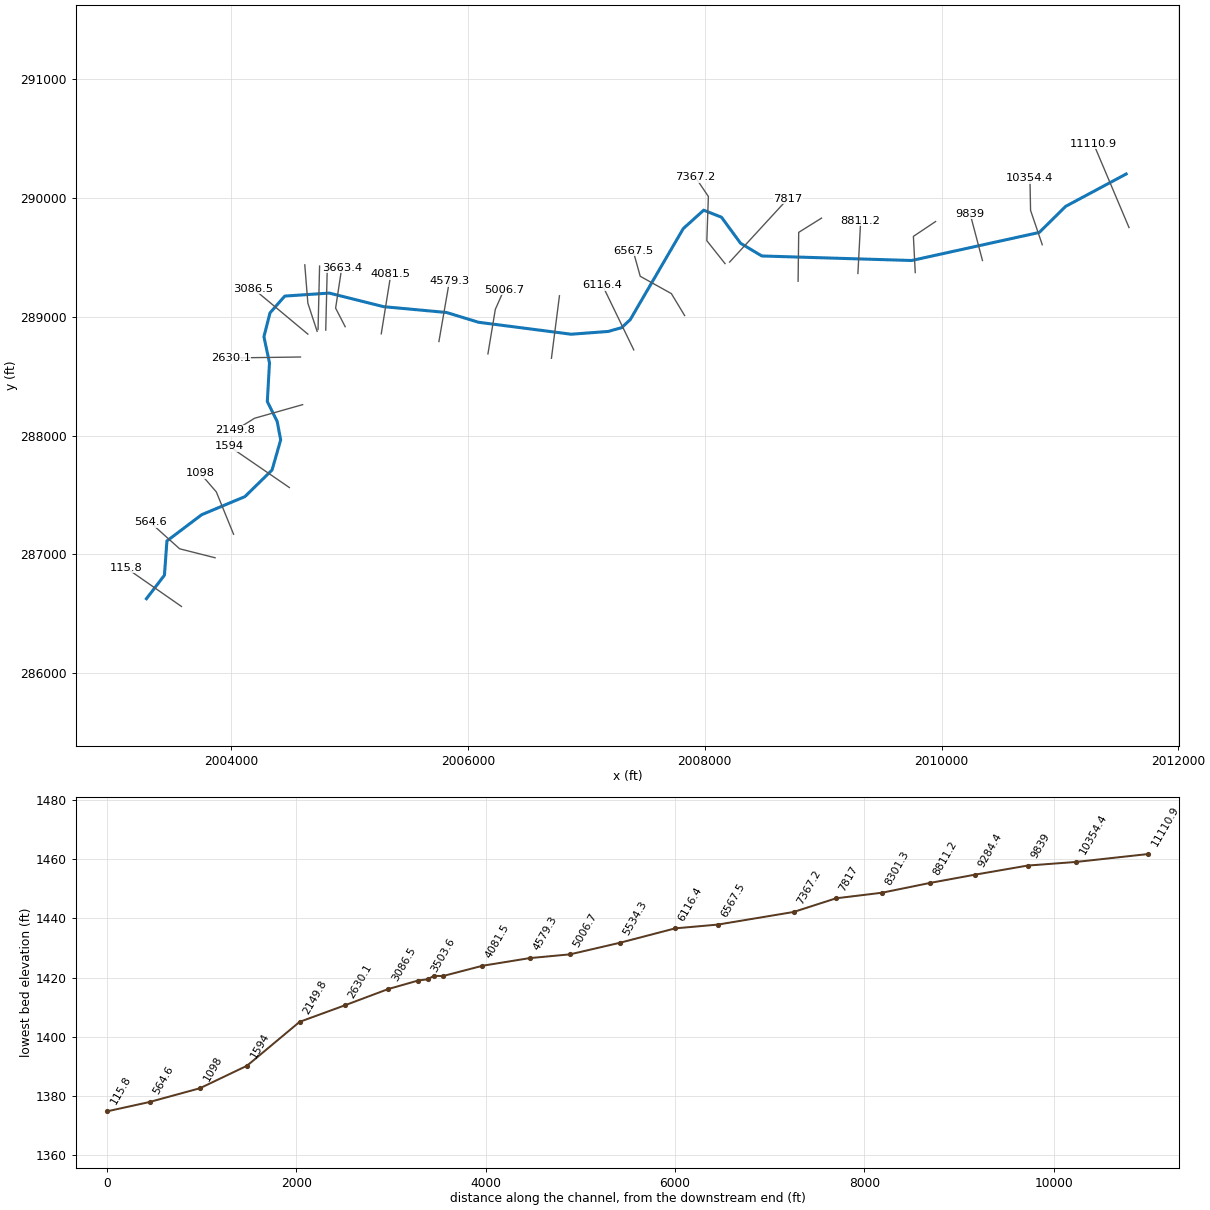
--- LICKCK2.prj (project) ---

Proj Title=LICKCK2
Current Plan=p01
Default Exp/Contr=0,0
English Units
Geom File=g01
Flow File=f01
Plan File=p01
BEGIN DESCRIPTION:
END DESCRIPTION:
DSS Export Rating Curves= 0
DSS Export Rating Curve Sorted= 0
DSS Export Volume Flow Curves= 0
DXF OffsetX= 0
DXF OffsetY= 0
DXF ScaleX= 0
DXF ScaleY= 0

--- LICKCK2.p01 (plan) ---

Plan Title=Floodplain
Program Version=4.00
Geom File=g01
Flow File=f01
K Sum by GR=0
Std Step Tol=0.01
Critical Tol=0.01
Num of Std Step Trials=20
Max Error Tol=0.3
Flow Tol Ratio=0.001
Split Flow NTrial=30
Split Flow Tol=0.02
Split Flow Ratio=0.02
Log Output Level=0
Friction Slope Method=1
Unsteady Friction Slope Method=2
Unsteady Bridges Friction Slope Method=1
Global Log Level=0
CheckData=False
Run HTab=0
Run UNet=0
Run PostProcess=0
UNET Theta=0
UNET Theta Warmup=0
UNET ZTol=0
UNET ZSATol=0
UNET MxIter=0
UNET MaxInSteps=0
UNET DtIC=0
UNET DtMin=0
UNET MaxCRTS=0
UNET WFStab=0
UNET SFStab=0
UNET WFX=0
UNET SFX=0
UNET DSS MLevel=0
UNET DZMax Abort=0
UNET Convert EG Bridges=0
UNET Use Existing IB Tables=0
UNET Froude Limit=0
UNET Froude Power=0
Write IC File=0
Echo Input=False
Echo Output=False
Write Detailed=0

--- LICKCK2.f01 (steady flow) ---

Flow Title=2010 USGS WV Regression Equation
Program Version=5.03
Number of Profiles= 1
Profile Names=P100yr
River Rch & RM=LICKCK2,Main            ,11110.9
4844.296
River Rch & RM=LICKCK2,Main            ,115.8
5306.431
Boundary for River Rch & Prof#=LICKCK2,Main            , 1
Up Type= 0
Dn Type= 1
Dn Known WS=1381
Set Internal Change=LICKCK2         ,Main            ,11110.9 , 1 , 3 ,1469
DSS Import GetInterval= 0
DSS Import GetPeak= 0
DSS Import FillOption= 0

--- LICKCK2.g01 (geometry) ---

Geom Title=LiDAR
Program Version=4.10

River Reach=LICKCK2         ,Main
Reach XY= 30
     2011559.887      290203.247     2011048.602      289930.678
     2010825.512       289711.06     2009747.387      289474.949
      2008482.63      289513.143     2008302.942      289619.914
     2008141.484      289839.532      2007991.31       289898.56
     2007818.567      289743.178     2007370.651      288976.685
     2007298.602      288909.844     2007184.887      288877.726
     2006872.387      288854.289     2006089.401      288954.984
     2005818.567      289037.449     2005288.186       289086.06
     2004828.984      289200.643     2004453.116       289175.47
     2004328.116      289033.976     2004276.901      288833.456
     2004323.776       288612.97     2004305.546      288287.449
      2004388.88      288119.914     2004418.394      287964.532
     2004345.477       287711.06     2004116.311      287487.102
     2003751.727      287335.192     2003457.456      287113.838
     2003436.623      286825.643     2003284.713      286627.727

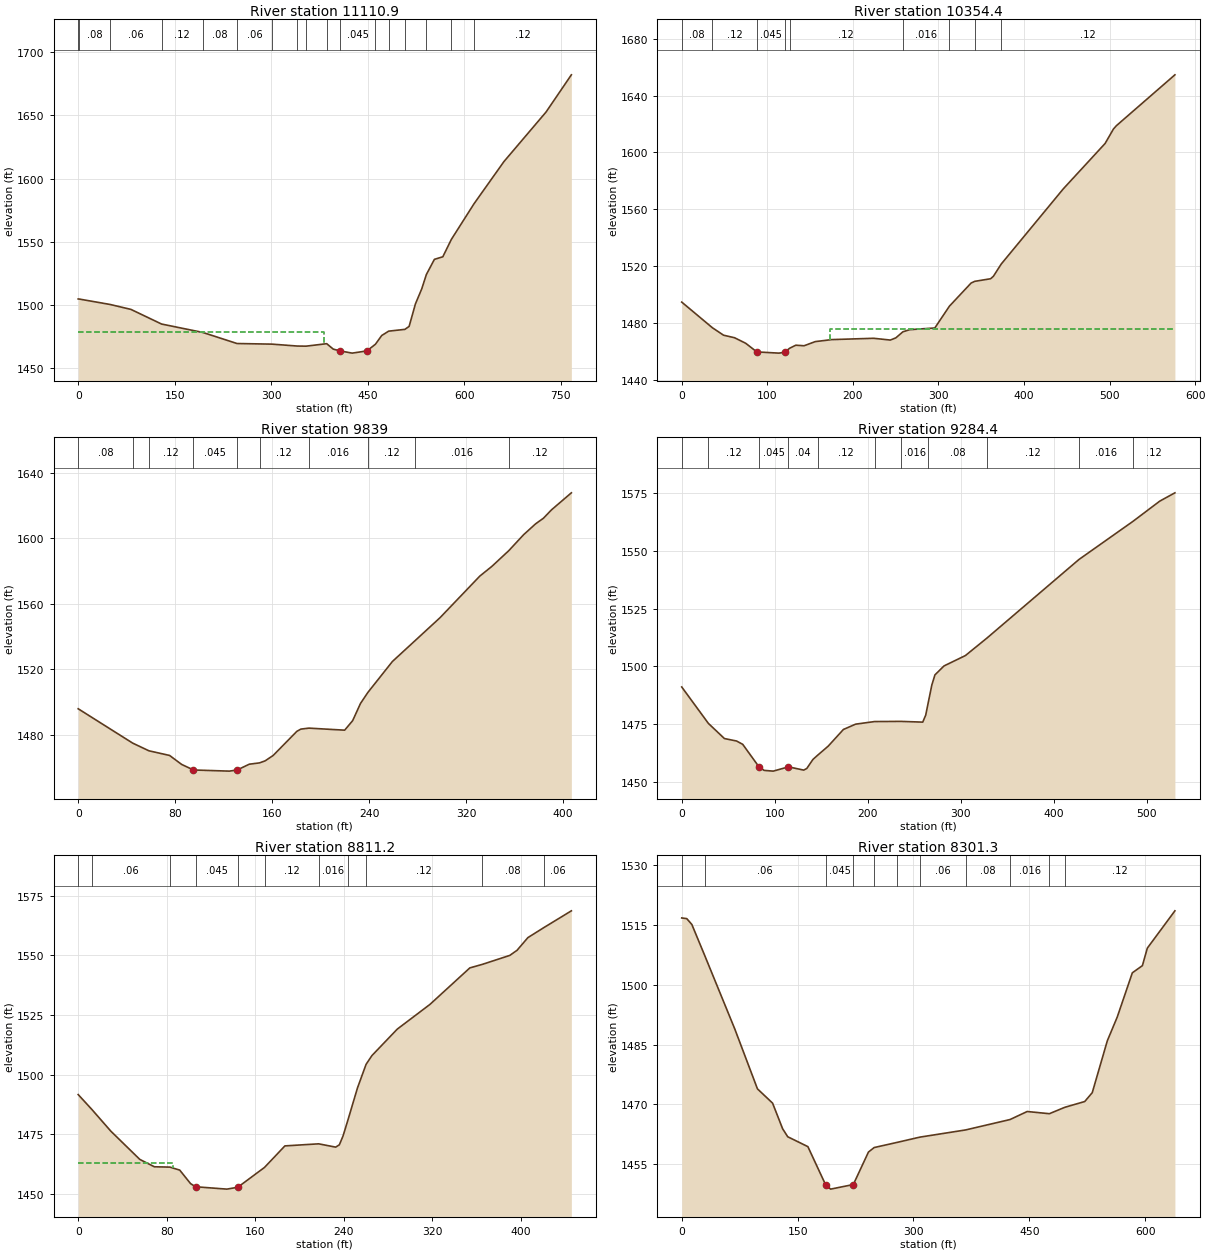
Type RM Length L Ch R = 1 ,11110.9 ,757.6,756.5,754.7
XS GIS Cut Line= 2
     2011583.793      289752.313     2011284.314      290458.042
#Sta/Elev= 30
       0 1504.65    1.271504.619   49.591500.298    81.9 1496.41  129.631484.804
  193.791478.132  246.881469.384  301.271468.897  340.781467.378  354.231467.294
  386.321469.258   396.4 1464.97   406.3 1463.62   425.9 1461.78   448.8 1463.54
     462  1468.8   471.8 1475.72  482.581479.173  507.761480.581   514.4 1482.92
   524.2 1500.74     534 1512.62  541.181523.956   553.7 1536.02   566.8 1538.05
  579.991551.742   615.41580.108   661.8 1613.41   727.3 1652.66   766.6 1682.08
#Mann= 17 ,-1 , 0
       0    .016       0    1.27     .08       0   49.59     .06       0
  129.63     .12       0  193.79     .08       0  246.88     .06       0
  301.27     .12       0  340.78     .06       0  354.23    .016       0
  386.32     .06       0   406.3    .045       0     462     .04       0
  482.58     .12       0  507.76    .016       0  541.18     .12       0
  579.99    .016       0   615.4     .12       0
#XS Ineff= 2 , 0
          382.36 1478.29
Permanent Ineff=
       F       F
Bank Sta=406.3,448.8
XS Rating Curve= 0 ,0
Exp/Cntr=0.3,0.1

Type RM Length L Ch R = 1 ,10354.4 ,516.9,515.4,513.7
XS GIS Cut Line= 3
     2010851.154      289607.782     2010752.196      289896.844
     2010746.987      290167.678
#Sta/Elev= 30
       0 1494.94    35.8 1476.96    48.8 1471.73    61.8 1469.91    74.8 1466.02
    87.8 1459.96   113.6 1459.12   120.3 1459.72  125.961462.495   133.3 1464.68
     143 1464.29     156  1467.2   175.5 1468.62   224.3 1469.54   243.8 1468.29
   250.3 1469.87  258.481474.096   266.5 1475.59   295.8 1476.78  312.861492.089
   338.2 1508.33  342.411509.515     361 1511.34   364.3 1513.11  373.38 1521.64
   445.9 1574.42   494.8 1606.31   504.6  1616.5   507.9 1618.75   576.4 1654.52
#Mann= 9 ,-1 , 0
       0     .08       0    35.8     .12       0    87.8    .045       0
   120.3     .04       0  125.96     .12       0  258.48    .016       0
  312.86     .12       0  342.41    .016       0  373.38     .12       0
#XS Ineff= 2 , 0
                          173.37         1476.18
Permanent Ineff=
       F       F
Bank Sta=87.8,120.3
XS Rating Curve= 0 ,0
Exp/Cntr=0.3,0.1

Type RM Length L Ch R = 1 ,9839    ,559.1,554.5,549.7
XS GIS Cut Line= 2
     2010345.946      289474.969     2010241.779      289868.198
#Sta/Elev= 30
       0 1495.96   44.89 1475.01   58.261470.313    75.4 1467.45    85.3 1461.99
    95.1 1458.58   124.7 1457.88   131.2  1458.6   141.1 1462.11  149.571462.916
   154.2 1464.16   160.8 1467.43   180.4  1482.2   183.7 1483.55  190.29 1484.14
   219.8 1482.89   226.4 1488.71   232.9 1499.27  239.041506.028   259.2 1524.85
  277.621537.379   298.5 1551.61   331.3    1577   341.2  1582.9  355.181592.519
   367.4 1602.26   377.3  1608.9   383.8 1612.35   390.4 1617.44   406.8 1627.84
#Mann= 10 ,-1 , 0
       0     .08       0   44.89     .06       0   58.26     .12       0
    95.1    .045       0   131.2     .04       0  149.57     .12       0
  190.29    .016       0  239.04     .12       0  277.62    .016       0
  355.18     .12       0
Bank Sta=95.1,131.2
XS Rating Curve= 0 ,0
Exp/Cntr=0.3,0.1

Type RM Length L Ch R = 1 ,9284.4  ,475.4,473.2,470.8
XS GIS Cut Line= 3
     2009778.237      289373.407     2009762.612      289678.094
     2009950.112      289803.094
#Sta/Elev= 30
       0 1491.15   28.651475.425    45.9 1468.88      59 1467.81    65.6 1466.37
   82.921456.744    88.6 1455.13    98.4 1454.81   114.8 1456.66   131.2 1455.25
   134.5 1455.96   141.1 1459.86  146.141461.665   157.5 1465.59   173.9 1472.81
     187 1475.09  207.411476.216  235.681476.288   259.2 1475.97   262.4 1478.99
     2651484.182     269 1492.03   272.3 1496.36   282.1 1500.24   305.1 1504.72
  328.141512.232   427.21546.203  485.541562.745   514.1  1571.4   530.4 1574.99
#Mann= 11 ,-1 , 0
       0     .08       0   28.65     .12       0   82.92    .045       0
   114.8     .04       0  146.14     .12       0  207.41     .06       0
  235.68    .016       0     265     .08       0  328.14     .12       0
   427.2    .016       0  485.54     .12       0
Bank Sta=82.92,114.8
XS Rating Curve= 0 ,0
Exp/Cntr=0.3,0.1

Type RM Length L Ch R = 1 ,8811.2  ,508.9,509.9,510.7
XS GIS Cut Line= 2
     2009293.862      289365.594       2009317.3      289810.907
#Sta/Elev= 30
       0 1491.64   12.191485.492    29.5 1476.32    55.7 1464.48    68.9 1461.39
   82.921461.253    91.8    1460   101.6 1454.34  106.131453.023   134.4 1452.03
   144.3 1452.82  168.471461.131   186.9 1470.14  217.431471.006   232.8 1469.62
   236.1 1470.59   239.4 1474.22  243.991481.149   252.5 1494.41  260.291504.309
   265.6 1507.99   288.5 1519.07     318  1529.4   354.1 1544.71  365.541546.209
   390.2 1549.94   396.8 1552.09   406.6  1557.4  420.991561.585   445.9 1568.62
#Mann= 11 ,-1 , 0
       0     .08       0   12.19     .06       0   82.92     .12       0
  106.13    .045       0   144.3     .04       0  168.47     .12       0
  217.43    .016       0  243.99     .08       0  260.29     .12       0
  365.54     .08       0  420.99     .06       0
#XS Ineff= 2 , 0
           85.66 1462.94
Permanent Ineff=
       F       F
Bank Sta=106.13,144.3
XS Rating Curve= 0 ,0
Exp/Cntr=0.3,0.1

Type RM Length L Ch R = 1 ,8301.3  ,500.8,484.3,467.7
XS GIS Cut Line= 3
     2008788.654       289300.49     2008793.862      289711.948
     2008986.571       289831.74
#Sta/Elev= 30
       0 1516.79     6.5 1516.62    13.1 1515.15   29.951507.268    68.6 1488.95
      98 1473.88   117.6 1470.29   130.6 1463.86   137.2 1461.85   163.3 1459.37
   186.2 1449.81   192.7  1448.7   222.1 1449.85   241.7 1458.01  249.151459.143
  278.761460.432   308.31461.757  367.381463.559  424.921466.169   447.2 1468.19
  475.921467.639   495.8 1469.24   521.7  1470.7   531.4 1472.92   550.9 1485.94
   563.8 1491.93   583.3 1503.02   596.3 1504.81   602.7 1509.21   638.4 1518.58
#Mann= 11 ,-1 , 0
       0     .08       0   29.95     .06       0   186.2    .045       0
   222.1     .04       0  249.15     .12       0  278.76     .08       0
   308.3     .06       0  367.38     .08       0  424.92    .016       0
  475.92     .08       0   495.8     .12       0
Bank Sta=186.2,222.1
XS Rating Curve= 0 ,0
Exp/Cntr=0.3,0.1

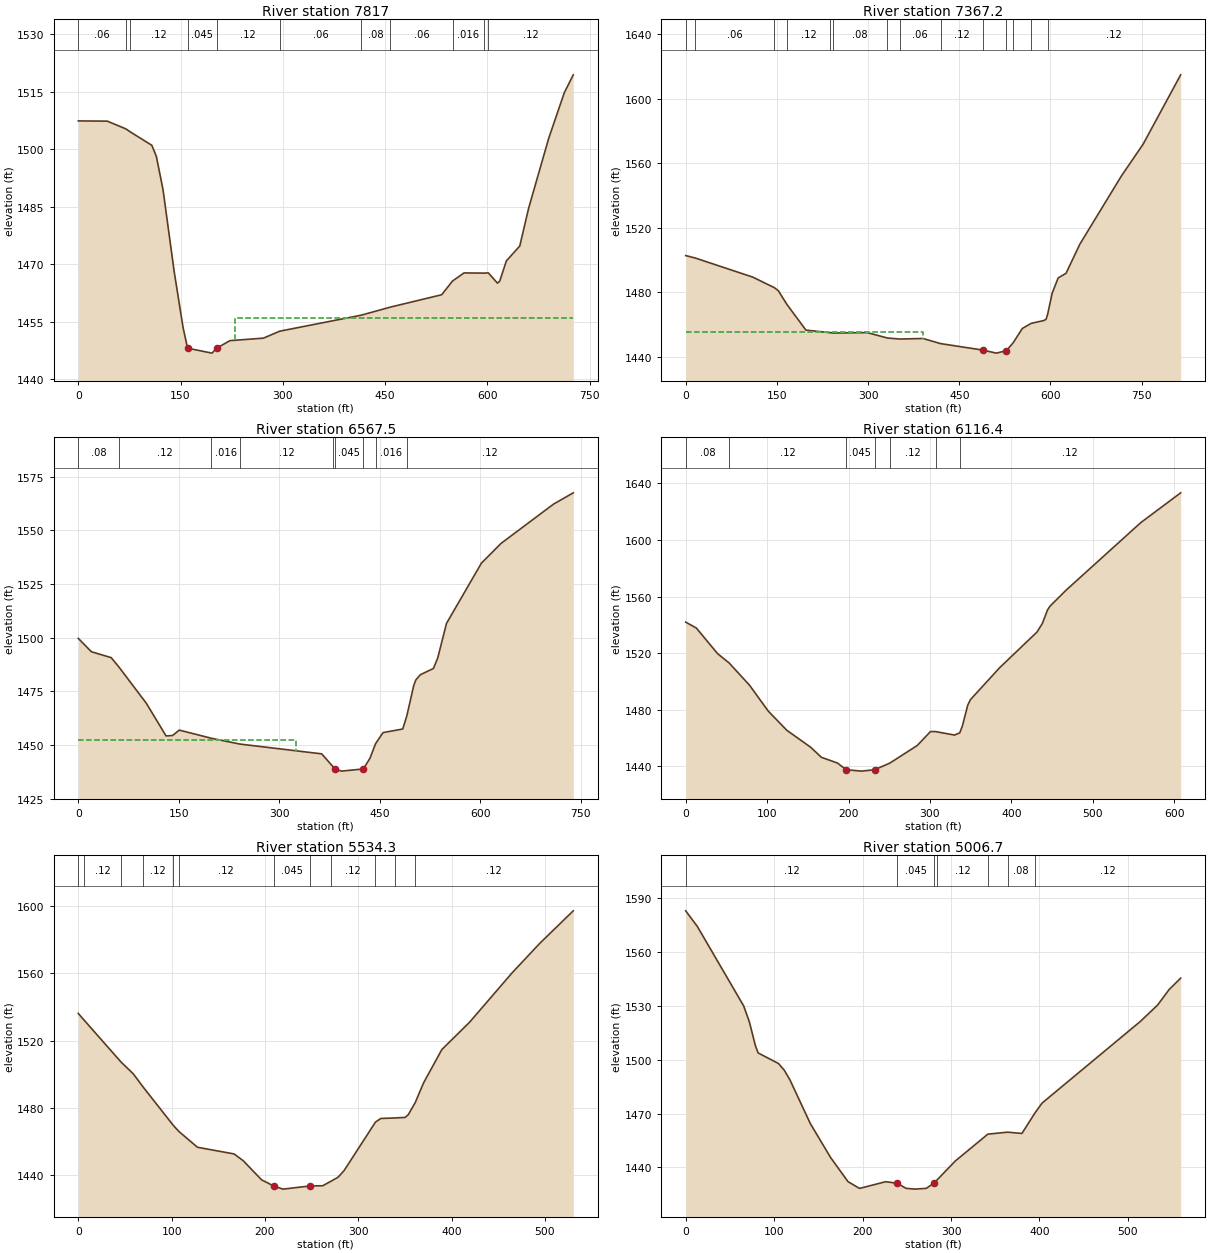
Type RM Length L Ch R = 1 ,7817    ,433.4,449.8,465.9
XS GIS Cut Line= 2
     2008210.529      289461.948     2008702.717      289995.803
#Sta/Elev= 30
       0 1507.34    42.5 1507.28   69.781505.266   76.181504.488   107.9 1500.98
   114.5 1498.12   124.3 1489.43   140.6 1468.17   153.7 1453.51   160.3  1448.1
   196.2 1446.82   202.8 1448.09   222.4 1450.07   271.5 1450.72  295.661452.544
  414.781456.696  457.711458.806   533.1 1462.04  548.951465.608   565.8 1467.72
   595.81467.672  601.451467.742   614.9 1465.06   618.2 1465.58     628 1470.87
   647.6 1474.72   660.7 1484.63   690.1 1502.81     713 1514.71   726.1 1519.35
#Mann= 11 ,-1 , 0
       0     .06       0   69.78     .08       0   76.18     .12       0
   160.3    .045       0   202.8     .12       0  295.66     .06       0
  414.78     .08       0  457.71     .06       0  548.95    .016       0
   595.8     .08       0  601.45     .12       0
#XS Ineff= 2 , 0
                          229.51         1455.95
Permanent Ineff=
       F       F
Bank Sta=160.3,202.8
XS Rating Curve= 0 ,0
Exp/Cntr=0.3,0.1

Type RM Length L Ch R = 1 ,7367.2  ,774.3,799.7,824.2
XS GIS Cut Line= 4
     2008171.467      289448.928     2008017.821      289641.636
     2008030.842      290014.032     2007921.467       290175.49
#Sta/Elev= 30
       0 1502.66   15.531501.188   110.3 1489.32  145.761482.788   152.4 1480.88
  166.641472.303   197.8 1456.45  237.711454.857  242.191454.637   298.8  1454.9
  331.791451.561  352.391450.924   390.3 1451.27  419.211448.093   488.3  1444.1
   511.2 1442.19   527.6 1443.76  538.68 1448.64   553.7 1457.48  568.231460.638
   589.7 1462.46   592.9 1463.34   595.41466.423   602.7 1479.27   612.6  1488.8
   625.6  1491.7   648.3 1509.75   716.6    1552   752.4 1571.77   814.1 1614.74
#Mann= 14 ,-1 , 0
       0    .016       0   15.53     .06       0  145.76     .08       0
  166.64     .12       0  237.71    .016       0  242.19     .08       0
  331.79     .12       0  352.39     .06       0  419.21     .12       0
   488.3    .045       0   527.6     .04       0  538.68     .12       0
  568.23    .016       0   595.4     .12       0
#XS Ineff= 2 , 0
          391.12 1455.51
Permanent Ineff=
       F       F
Bank Sta=488.3,527.6
XS Rating Curve= 0 ,0
Exp/Cntr=0.3,0.1

Type RM Length L Ch R = 1 ,6567.5  ,464.9,451.1,437.2
XS GIS Cut Line= 4
     2007830.321      289011.428     2007718.342      289196.323
     2007455.321      289342.157     2007395.425      289555.698
#Sta/Elev= 30
       0 1499.73    19.6  1493.5    49.1 1490.77   60.721486.364   101.5 1469.54
     131 1454.31   140.8 1454.53   150.7 1457.03  198.581453.233  241.011450.532
   363.3 1445.97  380.511439.864   382.9 1438.98   392.7 1437.93   425.4 1438.94
   435.2 1443.86  443.65  1450.7   454.8 1455.87   484.2 1457.54  490.341463.724
   500.6 1477.74   503.8 1480.39   510.4  1482.8     530 1485.72   536.5 1490.67
   549.5  1506.7   601.7 1534.79   631.1 1543.99   709.3 1562.24   738.7 1567.49
#Mann= 9 ,-1 , 0
       0     .08       0   60.72     .12       0  198.58    .016       0
  241.01     .12       0  380.51     .04       0   382.9    .045       0
   425.4     .12       0  443.65    .016       0  490.34     .12       0
#XS Ineff= 2 , 0
          325.28 1452.43
Permanent Ineff=
       F       F
Bank Sta=382.9,425.4
XS Rating Curve= 0 ,0
Exp/Cntr=0.3,0.1

Type RM Length L Ch R = 1 ,6116.4  ,595.1,582.1,569
XS GIS Cut Line= 2
     2007400.633      288722.365     2007135.008       289269.24
#Sta/Elev= 30
       0 1541.92    13.1 1537.74    39.2 1519.64    53.31513.102    78.4 1497.36
   101.3 1479.14   124.2 1465.51   153.6  1453.5   166.7  1446.4   186.3 1442.41
  197.191437.667   215.7 1436.65   232.1 1437.64  250.75 1442.32   284.4 1454.74
   300.7 1464.62  306.911464.604   330.1 1462.12  336.651463.696   339.9 1468.56
   346.5 1483.35   349.8 1487.18   385.7 1509.75   431.5 1534.88     438 1540.84
   444.5 1550.59   447.8 1553.36   467.4 1564.56   558.9 1612.16     608 1633.26
#Mann= 7 ,-1 , 0
       0     .08       0    53.3     .12       0  197.19    .045       0
   232.1     .04       0  250.75     .12       0  306.91    .016       0
  336.65     .12       0
Bank Sta=197.19,232.1
XS Rating Curve= 0 ,0
Exp/Cntr=0.3,0.1

Type RM Length L Ch R = 1 ,5534.3  ,528.4,527.6,526.7
XS GIS Cut Line= 2
     2006705.321      288652.053     2006773.029      289178.094
#Sta/Elev= 30
       0 1536.26    5.661532.628   45.961507.263    58.9 1500.35   69.78 1492.28
  101.561469.883  107.571466.195   127.7 1456.68     167 1452.71   176.8 1448.65
   196.4 1437.33   209.5 1433.64   219.4 1431.79   248.8 1433.71   261.9 1433.78
  270.761436.485   278.3 1438.85   284.8  1442.8  318.421471.615   324.1 1473.79
  339.171474.104   350.3 1474.42   353.6 1476.03  361.021483.211     370 1494.96
   389.6 1514.79   419.1  1530.9   464.9 1560.39   494.4 1577.85   530.4 1597.24
#Mann= 12 ,-1 , 0
       0     .08       0    5.66     .12       0   45.96     .08       0
   69.78     .12       0  101.56     .08       0  107.57     .12       0
   209.5    .045       0   248.8     .04       0  270.76     .12       0
  318.42    .016       0  339.17     .08       0  361.02     .12       0
Bank Sta=209.5,248.8
XS Rating Curve= 0 ,0
Exp/Cntr=0.3,0.1

Type RM Length L Ch R = 1 ,5006.7  ,427.5,427.4,427.1
XS GIS Cut Line= 3
     2006168.862      288688.511     2006231.362      289063.511
     2006304.279      289227.573
#Sta/Elev= 30
       0  1583.1    13.1 1574.45    65.6 1530.03    72.1 1521.01    78.7 1508.12
    81.9 1503.84   104.9 1497.94   111.4 1494.25     118  1488.7   140.9 1464.47
   163.9 1445.48   183.5 1432.07   196.6 1428.26   226.1 1432.02   239.2 1431.14
   249.1 1428.33   258.9 1427.87     272  1428.3  280.69 1431.23  284.561433.153
   304.8 1443.53  341.651458.535  363.961459.638   380.2 1458.92     3951470.408
     403 1475.87     514 1521.36   533.6 1530.53   546.6 1539.17   559.7 1545.55
#Mann= 7 ,-1 , 0
       0     .12       0   239.2    .045       0  280.69     .04       0
  284.56     .12       0  341.65    .016       0  363.96     .08       0
     395     .12       0
Bank Sta=239.2,280.69
XS Rating Curve= 0 ,0
Exp/Cntr=0.3,0.1

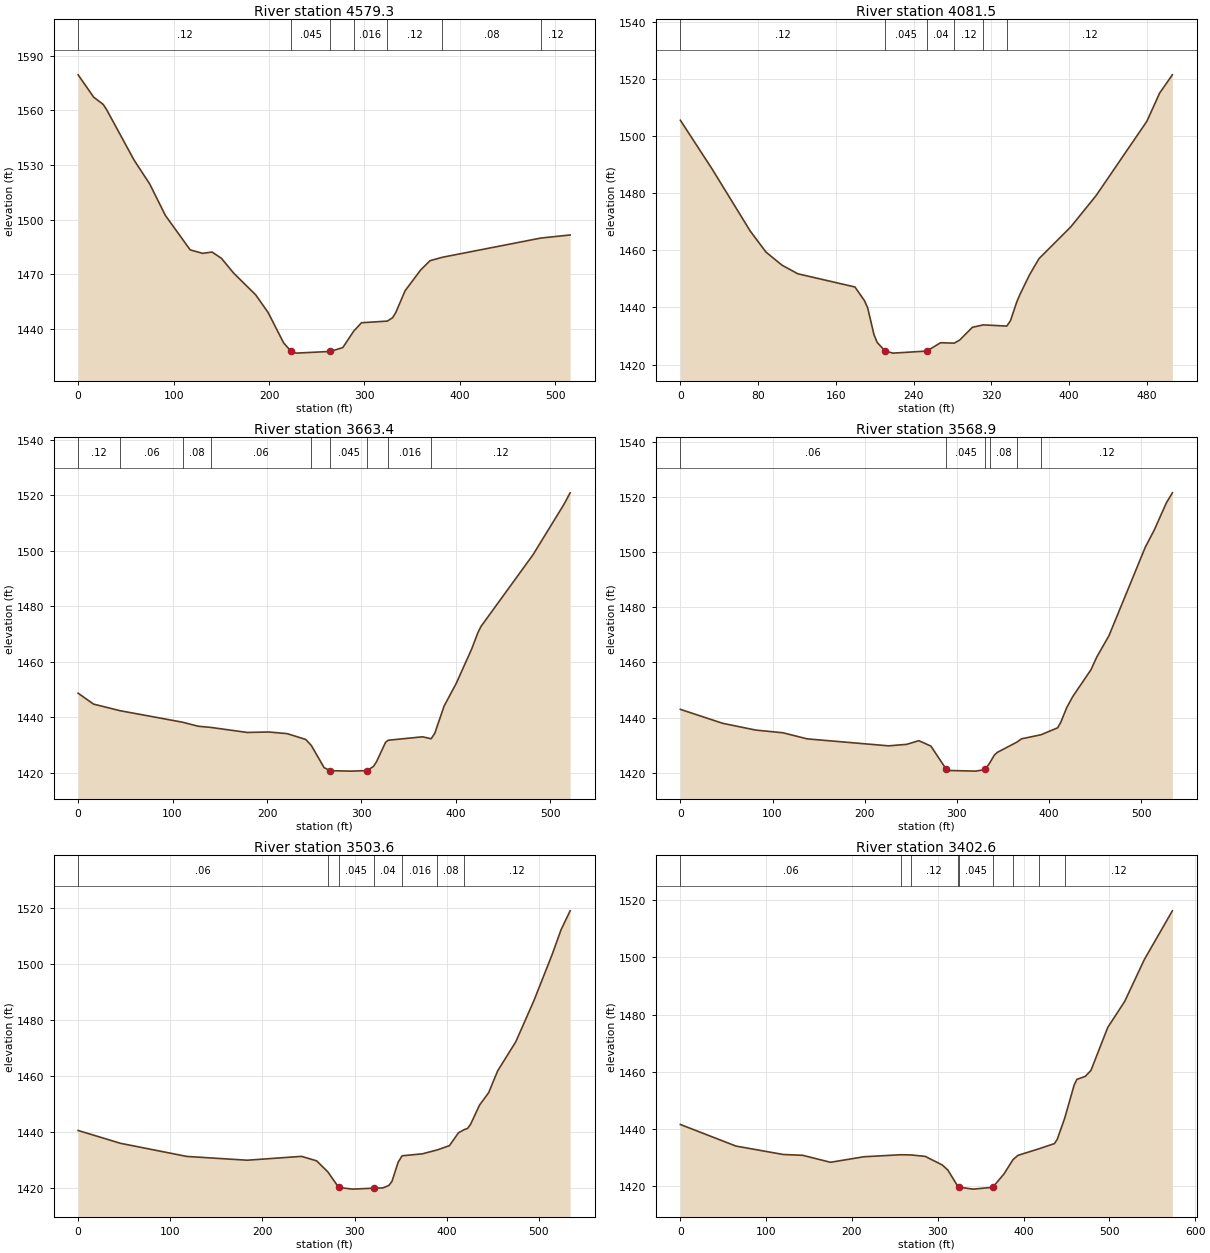
Type RM Length L Ch R = 1 ,4579.3  ,497.3,497.8,497.9
XS GIS Cut Line= 2
       2005754.8      288792.678     2005843.342       289300.49
#Sta/Elev= 30
       0  1579.5    16.3 1567.21    26.1 1563.32    29.4 1560.79    58.7 1532.58
      75 1519.54    91.4 1502.26   117.4 1483.32   130.5 1481.41   140.3 1482.15
   150.1 1478.69   163.1 1470.48     186 1458.64     199 1448.97   215.3 1432.24
  223.211427.491   228.4 1426.59   264.3 1427.52   277.3 1429.64  288.661438.616
   296.9 1443.29     3241444.188   329.5 1446.07   332.8 1448.88   342.6 1460.88
   358.9 1472.28   368.7 1477.38  381.761479.274  484.691489.804   515.5 1491.51
#Mann= 7 ,-1 , 0
       0     .12       0  223.21    .045       0   264.3     .04       0
  288.66    .016       0     324     .12       0  381.76     .08       0
  484.69     .12       0
Bank Sta=223.21,264.3
XS Rating Curve= 0 ,0
Exp/Cntr=0.3,0.1

Type RM Length L Ch R = 1 ,4081.5  ,417.8,418,418.2
XS GIS Cut Line= 2
     2005267.821      288857.782      2005348.55      289357.782
#Sta/Elev= 30
       0 1505.54    32.7 1488.46    71.9 1466.76    88.2 1459.36   104.6 1454.81
   120.9 1451.79   179.7 1447.17   189.5 1442.38   192.8  1439.9   199.3  1430.5
   202.6 1427.75  210.771424.736   218.9 1424.01  253.66 1424.73   267.9 1427.65
  281.941427.505   287.6  1428.6   300.6 1433.05  311.86  1433.9  336.051433.487
   339.8 1435.34   346.4 1442.02   349.6 1444.56   359.4  1451.4   369.2  1457.1
   401.9 1468.21     428 1479.18   480.3 1505.21   493.4 1515.07   506.5 1521.45
#Mann= 6 ,-1 , 0
       0     .12       0  210.77    .045       0  253.66     .04       0
  281.94     .12       0  311.86    .016       0  336.05     .12       0
Bank Sta=210.77,253.66
XS Rating Curve= 0 ,0
Exp/Cntr=0.3,0.1

Type RM Length L Ch R = 1 ,3663.4  ,91.5,94.5,97.3
XS GIS Cut Line= 3
     2004963.133      288917.678     2004882.404      289073.928
     2004934.487      289415.073
#Sta/Elev= 30
       0 1448.64    16.3  1444.7   44.411442.319  110.571438.169     127 1436.72
  140.271436.302   179.1 1434.47   201.9 1434.64   221.4 1434.04     241 1431.95
  246.951429.772   260.5 1421.77     267 1420.68   289.8 1420.52   306.1 1420.73
   312.6 1422.18   315.9 1423.86   325.6 1430.94  328.421431.666   364.7  1432.9
  373.841432.202   377.7 1434.18   387.5 1443.97   400.5 1452.25   416.8 1464.63
   423.3 1470.46   426.6 1472.71   481.9 1498.68   514.5 1516.79     521 1520.92
#Mann= 9 ,-1 , 0
       0     .12       0   44.41     .06       0  110.57     .08       0
  140.27     .06       0  246.95     .08       0     267    .045       0
   306.1     .04       0  328.42    .016       0  373.84     .12       0
Bank Sta=267,306.1
XS Rating Curve= 0 ,0
Exp/Cntr=0.3,0.1

Type RM Length L Ch R = 1 ,3568.9  ,65.4,65.3,65.4
XS GIS Cut Line= 2
     2004799.071      288889.032     2004812.092      289422.886
#Sta/Elev= 30
       0 1443.01    45.9 1437.94    81.9 1435.48   111.4 1434.51   137.6  1432.3
     226 1429.77   245.7 1430.32   258.8 1431.64   271.9 1429.68   288.3 1421.43
   291.6 1420.83   320.8  1420.6   330.9 1421.21   335.81423.585   340.7 1426.39
     344  1427.4  365.341431.131   370.2 1432.31  391.351433.787   409.5 1436.31
   412.8 1438.27   419.4 1443.68   425.9 1447.66   445.6 1457.36   452.1 1462.09
   465.2 1469.73   504.5 1501.73   514.4 1508.09   527.5 1517.91     534 1521.54
#Mann= 6 ,-1 , 0
       0     .06       0   288.3    .045       0   330.9     .04       0
   335.8     .08       0  365.34    .016       0  391.35     .12       0
Bank Sta=288.3,330.9
XS Rating Curve= 0 ,0
Exp/Cntr=0.3,0.1

Type RM Length L Ch R = 1 ,3503.6  ,98.7,101,103.4
XS GIS Cut Line= 2
     2004733.967       288894.24     2004746.987      289428.094
#Sta/Elev= 30
       0 1440.45    45.9 1435.86   117.9 1431.16   183.5  1429.8   242.4 1431.18
   258.8 1429.59  271.04 1425.63  282.851420.036   298.1 1419.45   321.1  1419.8
   330.9 1419.89   337.4  1420.8   340.7 1422.28   347.3 1429.06  351.641431.393
   373.5 1432.08  389.681433.482     403 1435.01   412.8 1439.62  419.231440.781
   422.6 1441.17   425.9 1442.62   435.7 1449.55   445.6    1454   455.4 1461.82
     475 1472.19   494.7 1486.94   514.4 1503.37   524.2 1512.35     534 1519.09
#Mann= 7 ,-1 , 0
       0     .06       0  271.04     .12       0  282.85    .045       0
   321.1     .04       0  351.64    .016       0  389.68     .08       0
  419.23     .12       0
Bank Sta=282.85,321.1
XS Rating Curve= 0 ,0
Exp/Cntr=0.3,0.1

Type RM Length L Ch R = 1 ,3402.6  ,298.2,316.1,334.2
XS GIS Cut Line= 3
     2004726.154      288878.615     2004648.029      289115.594
     2004621.987      289438.511
#Sta/Elev= 30
       0  1441.6    64.8 1434.06   119.9 1431.12   142.6 1430.83     175  1428.4
   213.9 1430.33  256.681431.029  268.891430.968   285.5 1430.45   305.2 1427.47
   311.7 1425.72  323.041420.185   324.8  1419.7   341.2 1419.02   364.1 1419.65
   377.2 1424.32  387.761429.339   393.5 1430.82  418.281433.138     436 1434.92
   439.3 1436.42  447.911443.724     459 1455.38   462.2 1457.37     472 1458.41
   478.6  1460.5   498.2 1475.52   517.9 1484.58   540.8  1499.2   573.5 1516.24
#Mann= 9 ,-1 , 0
       0     .06       0  256.68     .08       0  268.89     .12       0
  323.04     .04       0   324.8    .045       0   364.1     .04       0
  387.76    .016       0  418.28     .08       0  447.91     .12       0
Bank Sta=324.8,364.1
XS Rating Curve= 0 ,0
Exp/Cntr=0.3,0.1

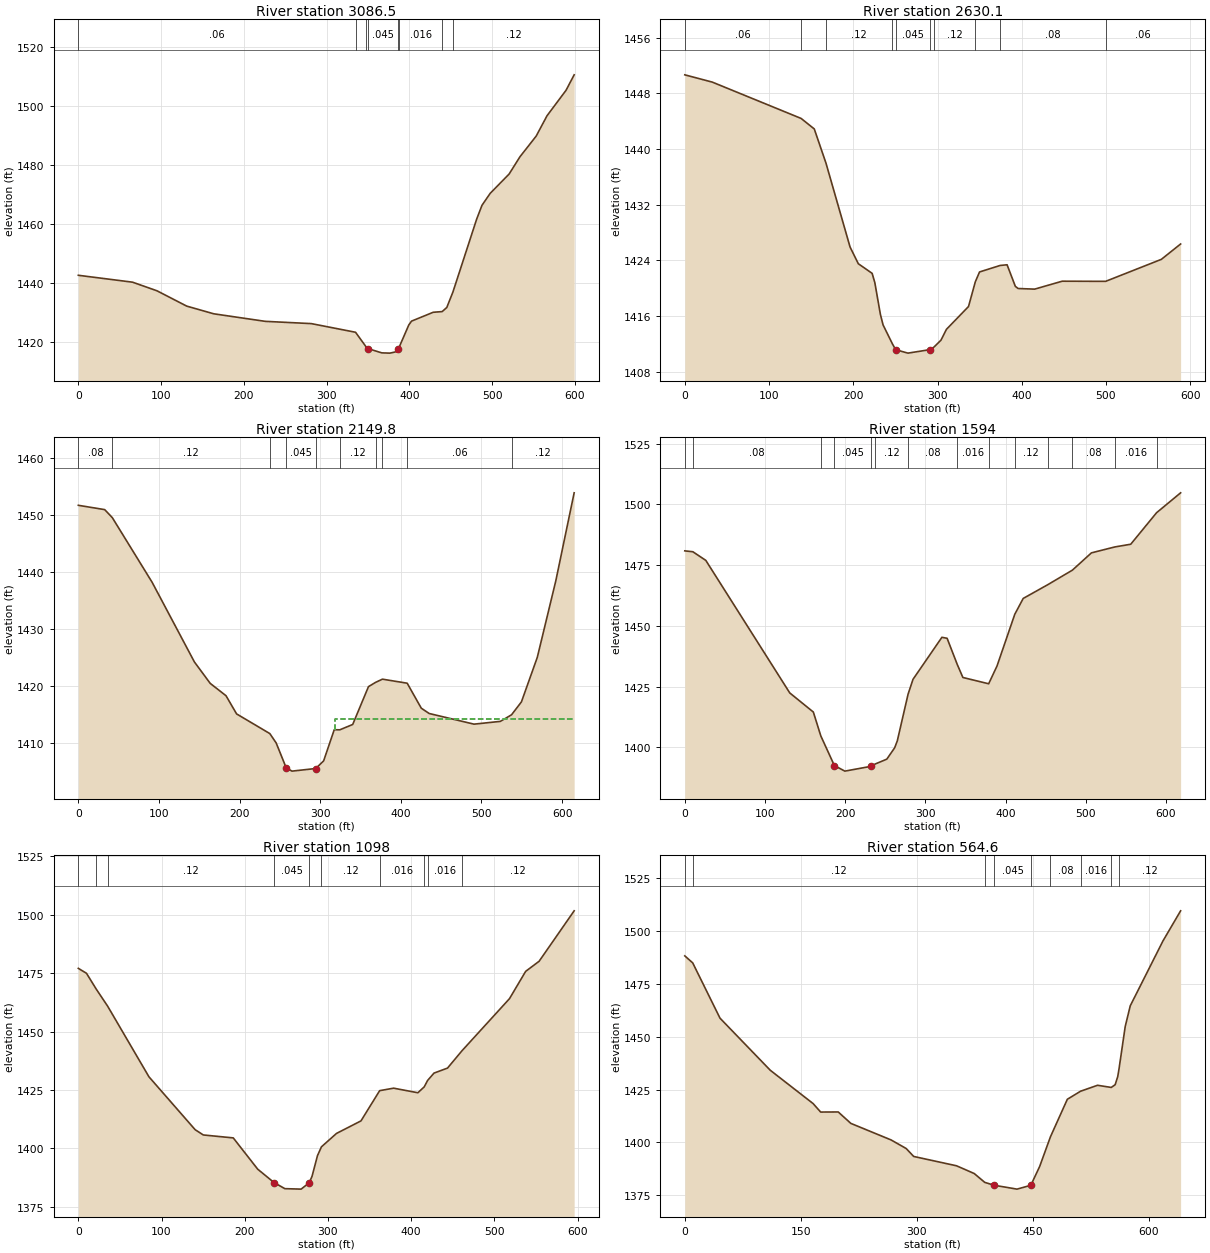
Type RM Length L Ch R = 1 ,3086.5  ,440.3,456.3,471.9
XS GIS Cut Line= 2
     2004648.029      288855.178     2004187.092       289237.99
#Sta/Elev= 30
       0 1442.57    65.5 1440.23      95 1437.31     131  1432.1   163.7 1429.49
   225.9 1426.93   281.6 1426.16  335.011423.225  347.25 1418.47   350.3 1417.65
   366.7 1416.23   376.5 1416.14   383.1 1416.54   386.4  1417.5  388.111418.408
   399.4 1425.72   402.7 1427.01   428.9 1430.01  439.711430.243   445.3 1431.64
   452.71436.893   481.3 1461.57   487.8 1466.32   497.7 1470.38   520.6 1476.95
   533.7 1482.81   553.3 1489.82   566.4 1496.73   589.4 1505.38   599.2 1510.63
#Mann= 8 ,-1 , 0
       0     .06       0  335.01     .12       0  347.25     .04       0
   350.3    .045       0   386.4     .04       0  388.11    .016       0
  439.71     .06       0   452.7     .12       0
Bank Sta=350.3,386.4
XS Rating Curve= 0 ,0
Exp/Cntr=0.3,0.1

Type RM Length L Ch R = 1 ,2630.1  ,474.1,480.3,486.3
XS GIS Cut Line= 2
     2004585.529      288662.469     2003996.987      288654.657
#Sta/Elev= 30
       0 1450.67    32.7 1449.62  138.071444.402   153.7 1442.89  167.611437.971
   196.2 1425.91     206 1423.51   222.4 1422.13   225.6 1420.79   232.2 1416.23
   235.4 1414.71  246.531411.977  250.341411.152   264.9 1410.66     291 1411.16
  295.771411.529   304.1 1412.52   310.6 1414.08   336.8 1417.36  344.861420.904
   349.9 1422.33   374.41423.265   382.6 1423.36   392.4 1420.26   395.7 1419.95
   415.3 1419.86     448    1421  499.581420.979   565.7 1424.14   588.6 1426.35
#Mann= 10 ,-1 , 0
       0     .06       0  138.07     .08       0  167.61     .12       0
  246.53     .04       0  250.34    .045       0     291     .04       0
  295.77     .12       0  344.86    .016       0   374.4     .08       0
  499.58     .06       0
Bank Sta=250.34,291
XS Rating Curve= 0 ,0
Exp/Cntr=0.3,0.1

Type RM Length L Ch R = 1 ,2149.8  ,574.8,555.8,536.3
XS GIS Cut Line= 3
     2004603.758      288261.428     2004197.508      288146.844
     2004033.446      288045.282
#Sta/Elev= 30
       0 1451.73    32.7 1450.97   42.171449.558    91.6 1438.19     144 1424.21
   163.6 1420.45   183.2 1418.28   196.3 1415.09  237.481411.638   245.4 1409.99
  257.791405.629     265 1405.04   294.5  1405.5   304.3 1406.85   317.4 1412.31
  324.321412.295   340.3 1413.23   359.9 1419.88  368.621420.624  377.211421.191
   407.91420.483   425.4 1416.09   435.2 1415.16   490.8 1413.29   523.5 1413.78
  537.361414.937   549.6  1417.2   569.3 1425.03   592.2 1438.44     615 1453.92
#Mann= 10 ,-1 , 0
       0     .08       0   42.17     .12       0  237.48     .04       0
  257.79    .045       0   294.5     .08       0  324.32     .12       0
  368.62     .08       0  377.21    .016       0   407.9     .06       0
  537.36     .12       0
#XS Ineff= 2 , 0
                          317.85         1414.19
Permanent Ineff=
       F       F
Bank Sta=257.79,294.5
XS Rating Curve= 0 ,0
Exp/Cntr=0.3,0.1

Type RM Length L Ch R = 1 ,1594    ,508.8,496.1,482.9
XS GIS Cut Line= 2
     2004491.779      287563.511     2003981.362      287912.469
#Sta/Elev= 30
       0  1480.9   10.061480.535    26.2 1476.98   130.9  1422.4   160.3 1414.53
  169.591404.724   186.5 1392.51   199.6  1390.2   232.3 1392.18  237.191393.096
   251.9 1395.13   261.7 1399.81     265 1402.66  278.391421.833   284.6 1428.01
   320.6  1445.3   327.1 1444.91  339.911434.005   346.8 1428.76  378.931426.171
   389.3 1433.46  411.481454.779     422 1461.31  452.561466.958  483.341472.958
   507.1 1480.08  536.361482.524   556.1 1483.63  588.271496.596   618.3  1504.8
#Mann= 14 ,-1 , 0
       0    .016       0   10.06     .08       0  169.59     .12       0
   186.5    .045       0   232.3     .04       0  237.19     .12       0
  278.39     .08       0  339.91    .016       0  378.93     .08       0
  411.48     .12       0  452.56    .016       0  483.34     .08       0
  536.36    .016       0  588.27     .12       0
Bank Sta=186.5,232.3
XS Rating Curve= 0 ,0
Exp/Cntr=0.3,0.1

Type RM Length L Ch R = 1 ,1098    ,522.9,533.4,543.3
XS GIS Cut Line= 3
     2004020.425      287170.282     2003874.592      287527.053
     2003736.571      287685.907
#Sta/Elev= 30
       0 1477.08     9.8 1474.97   21.511468.208   35.23  1460.9    84.9 1430.66
   140.4 1408.04   150.2 1405.79   186.2 1404.53   215.6 1391.14   235.2 1385.43
   248.2 1382.81   267.8 1382.61   277.6 1385.39   280.9 1388.12   287.4 1396.92
  292.181400.715   310.3 1406.45   339.7 1411.81  362.151424.744   378.9 1425.81
   408.1 1423.85  415.721426.377  419.781429.121   427.5 1432.27   443.7  1434.4
  461.041441.802   518.2 1464.12   537.6 1475.79   553.8 1480.12   595.9  1501.7
#Mann= 10 ,-1 , 0
       0     .06       0   21.51     .08       0   35.23     .12       0
   235.2    .045       0   277.6     .04       0  292.18     .12       0
  362.15    .016       0  415.72     .08       0  419.78    .016       0
  461.04     .12       0
Bank Sta=235.2,277.6
XS Rating Curve= 0 ,0
Exp/Cntr=0.3,0.1

Type RM Length L Ch R = 1 ,564.6   ,446.1,448.9,451.6
XS GIS Cut Line= 3
     2003864.175      286972.365     2003564.696      287047.886
       2003317.3       287269.24
#Sta/Elev= 30
       0 1488.28   10.231484.961    45.5 1458.81   110.5 1434.16   165.8 1418.42
   175.6  1414.4   198.3 1414.44   214.6 1409.04   266.6 1401.21   286.1 1397.16
   295.8  1393.4   351.2 1388.98     374 1385.33  387.721381.124     400 1379.77
   429.3 1377.94  447.191379.745   458.6 1388.64   472.61402.722   494.4 1420.45
  511.521424.255   533.4 1427.06  551.151426.045   556.2 1427.34   559.5 1431.13
  561.191434.822   569.2 1454.87   575.7 1464.65     618 1495.36   640.8 1509.59
#Mann= 9 ,-1 , 0
       0     .06       0   10.23     .12       0  387.72     .04       0
     400    .045       0  447.19     .12       0   472.6     .08       0
  511.52    .016       0  551.15     .08       0  561.19     .12       0
Bank Sta=400,447.19
XS Rating Curve= 0 ,0
Exp/Cntr=0.3,0.1

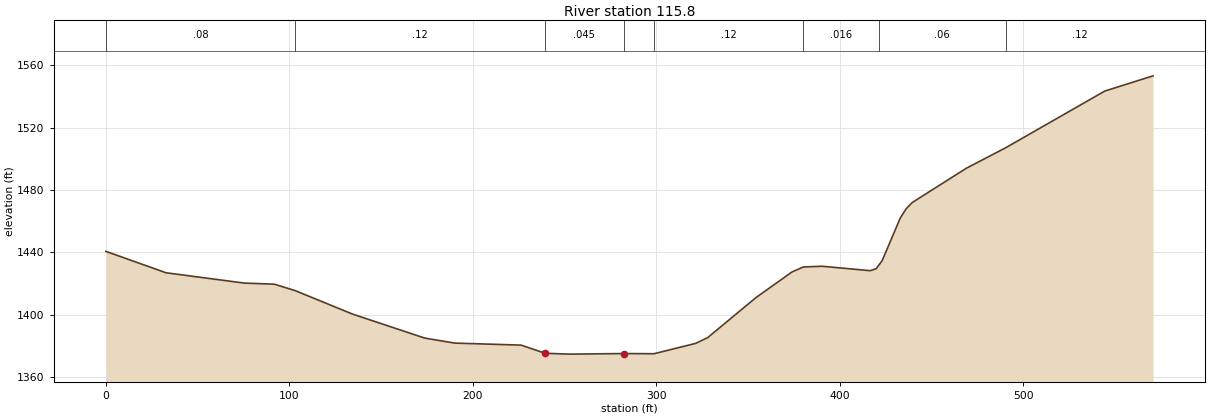
Type RM Length L Ch R = 1 ,115.8   ,118.3,115.8,113
XS GIS Cut Line= 2
     2003580.168      286562.433     2003111.418      286887.954
#Sta/Elev= 30
       0 1440.66    32.8 1426.93    75.4 1420.33    91.8 1419.61  103.141415.505
   134.5 1400.42   173.8 1385.05   190.2 1381.85   226.3 1380.55   239.4 1375.32
   252.6 1374.78   282.1 1375.14  298.711375.031   321.4 1381.66     328 1385.39
   354.2 1410.94   373.9 1427.45  380.08 1430.65   390.3 1431.12   416.5 1428.28
   419.8 1429.52  421.081431.564   423.1 1434.79   432.9 1461.95   436.2 1468.07
   439.5 1472.01     469 1493.99   490.41507.091   544.4 1543.43   570.7  1553.2
#Mann= 8 ,-1 , 0
       0     .08       0  103.14     .12       0   239.4    .045       0
   282.1     .04       0  298.71     .12       0  380.08    .016       0
  421.08     .06       0   490.4     .12       0
Bank Sta=239.4,282.1
XS Rating Curve= 0 ,0
Exp/Cntr=0.3,0.1

Chan Stop Cuts=-1
Use User Specified Reach Order=0
Composite Channel Slope=5